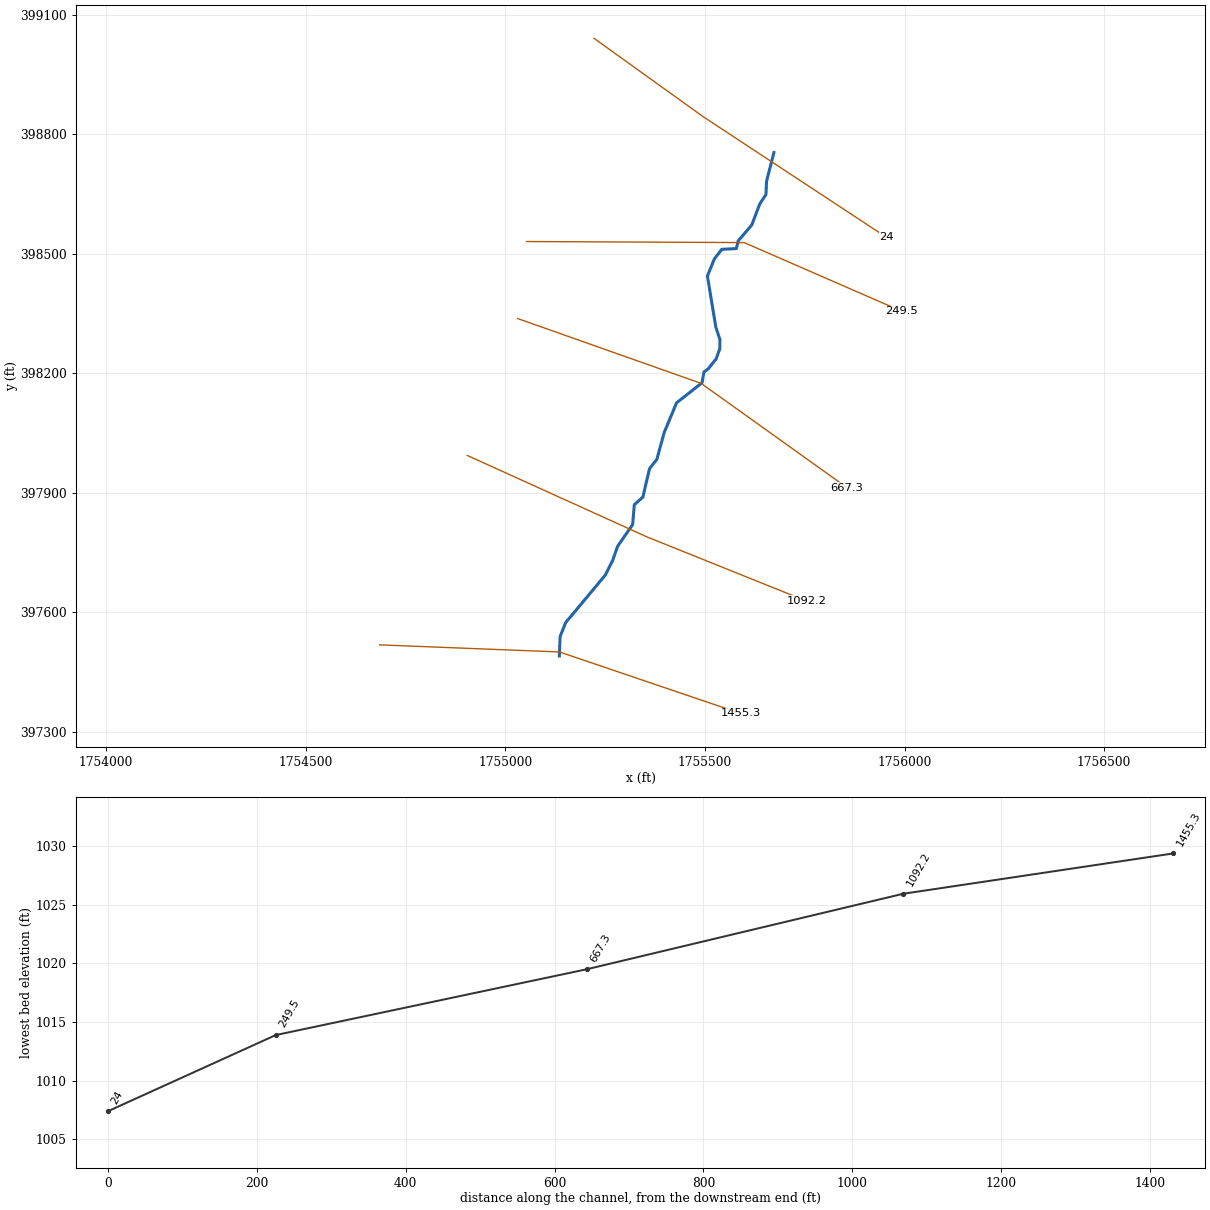
--- NP14.prj (project) ---

Proj Title=NP14
Current Plan=p01
Default Exp/Contr=0,0
English Units
Geom File=g01
Flow File=f01
Plan File=p01
BEGIN DESCRIPTION:
END DESCRIPTION:
DSS Export Rating Curves= 0
DSS Export Rating Curve Sorted= 0
DSS Export Volume Flow Curves= 0
DXF OffsetX= 0
DXF OffsetY= 0
DXF ScaleX= 0
DXF ScaleY= 0

--- NP14.p01 (plan) ---

Plan Title=Floodplain
Program Version=4.00
Geom File=g01
Flow File=f01
K Sum by GR=0
Std Step Tol=0.01
Critical Tol=0.01
Num of Std Step Trials=20
Max Error Tol=0.3
Flow Tol Ratio=0.001
Split Flow NTrial=30
Split Flow Tol=0.02
Split Flow Ratio=0.02
Log Output Level=0
Friction Slope Method=1
Unsteady Friction Slope Method=2
Unsteady Bridges Friction Slope Method=1
Global Log Level=0
CheckData=False
Run HTab=0
Run UNet=0
Run PostProcess=0
UNET Theta=0
UNET Theta Warmup=0
UNET ZTol=0
UNET ZSATol=0
UNET MxIter=0
UNET MaxInSteps=0
UNET DtIC=0
UNET DtMin=0
UNET MaxCRTS=0
UNET WFStab=0
UNET SFStab=0
UNET WFX=0
UNET SFX=0
UNET DSS MLevel=0
UNET DZMax Abort=0
UNET Convert EG Bridges=0
UNET Use Existing IB Tables=0
UNET Froude Limit=0
UNET Froude Power=0
Write IC File=0
Echo Input=False
Echo Output=False
Write Detailed=0

--- NP14.f01 (steady flow) ---

Flow Title=NFF Regression Equation
Program Version=4.00
Number of Profiles=1
Profile Names=P100yr
River Rch & RM=NP14,Main      ,1455.3
478.3275
River Rch & RM=NP14,Main      ,1092.2
489.6020
River Rch & RM=NP14,Main      ,24
538.2984
River Rch & RM=NP14,Main      ,24
538.2984
Boundary for River Rch & Prof#=NP14,Main      ,1
Up Type=0
Dn Type=3
Dn Slope=0.021032

--- NP14.g01 (geometry) ---

Geom Title=USGS 3m DEM
Program Version=4.00

River Reach=NP14     ,Main
Reach XY= 30
     1755135.226      397489.960     1755137.149      397538.671
     1755151.051      397573.665     1755250.153      397692.723
     1755268.878      397730.174     1755281.362      397765.545
     1755318.814      397819.642     1755322.975      397869.577
     1755344.417      397888.618     1755361.096      397960.131
     1755379.387      397983.425     1755398.102      398051.536
     1755428.913      398125.406     1755492.690      398175.612
     1755497.455      398202.867     1755508.102      398210.594
     1755527.920      398235.768     1755537.204      398261.031
     1755537.401      398284.477     1755527.082      398315.767
     1755506.188      398443.544     1755523.269      398486.246
     1755542.328      398510.733     1755578.577      398512.382
     1755583.229      398531.822     1755617.214      398571.650
     1755637.141      398624.315     1755652.799      398648.513
     1755654.222      398681.252     1755672.726      398753.845

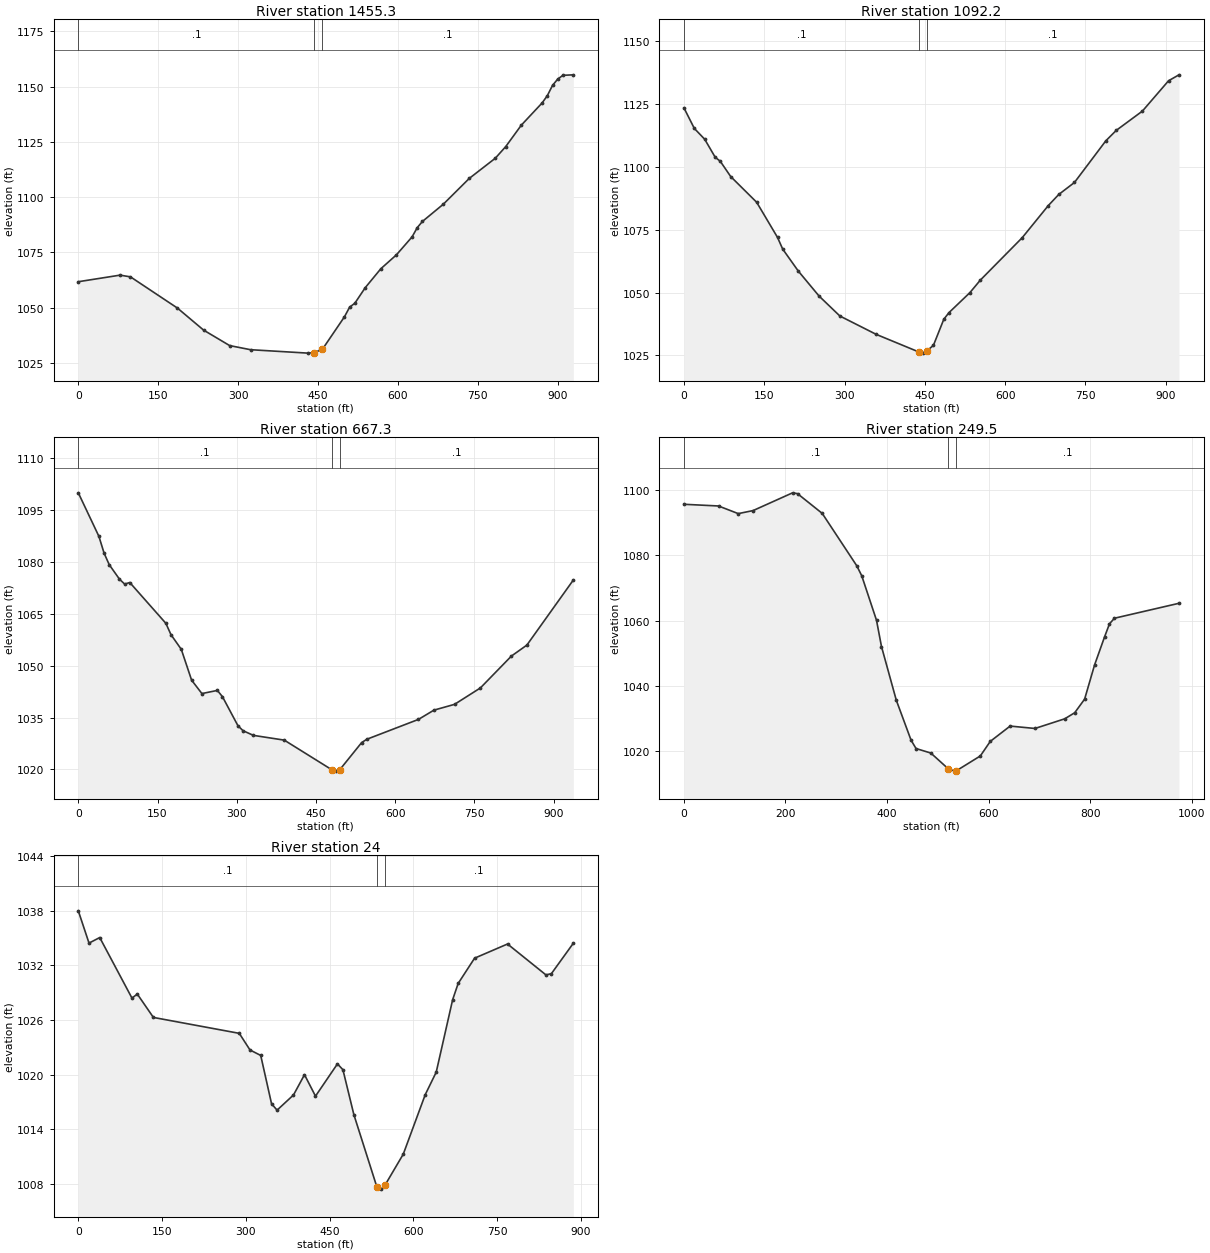
Type RM Length L Ch R = 1 ,1455.3,371.87,363.05,360.909
XS GIS Cut Line= 3
     1754685.140      397517.732     1755135.621      397499.952
     1755588.732      397345.778
#Sta/Elev= 30
       0 1061.68    78.4 1064.66    98.0 1063.88   186.2 1049.74   235.2 1039.79
   284.2 1032.77   323.4 1030.91   431.2 1029.36   443.3 1029.62   458.3 1031.09
   499.7 1045.79   509.4 1050.16   519.2 1051.94   538.7 1058.97   568.0 1067.55
   597.3 1073.85   626.7 1081.98   636.4 1086.17   646.2 1088.98   685.3 1096.76
   734.1 1108.45   782.9 1117.57   802.5 1122.84   831.8 1132.55   870.8 1142.59
   880.6 1145.89   890.4 1150.56   900.2 1153.42   909.9 1155.11   929.5 1155.33
#Mann= 3 , 0 , 0
       0     0.1       0   443.3   0.045       0   458.3     0.1       0
Bank Sta=   443.3,   458.3
Exp/Cntr=0.3,0.1

Type RM Length L Ch R = 1 ,1092.2,421.429,424.92,420.185
XS GIS Cut Line= 3
     1754904.440      397993.314     1755355.274      397788.488
     1755753.773      397627.938
#Sta/Elev= 30
       0 1123.45    19.4 1115.26    38.8 1110.96    58.3 1103.84    68.0 1102.17
    87.4 1096.12   135.9 1085.90   174.8 1071.94   184.5 1067.29   213.6 1058.56
   252.4 1048.62   291.3 1040.68   359.3 1033.37   439.2 1026.35   446.6 1025.92
   454.2 1026.87   466.1 1029.03   485.5 1039.40   495.2 1042.04   534.2 1049.97
   553.8 1054.97   631.9 1071.81   680.7 1084.60   700.2 1089.00   729.5 1093.77
   788.1 1110.33   807.6 1114.48   856.5 1122.16   905.3 1134.21   924.8 1136.57
#Mann= 3 , 0 , 0
       0     0.1       0   439.2   0.045       0   454.2     0.1       0
Bank Sta=   439.2,   454.2
Exp/Cntr=0.3,0.1

Type RM Length L Ch R = 1 ,667.3,380.038,417.813,429.473
XS GIS Cut Line= 3
     1755030.895      398336.851     1755490.483      398174.100
     1755856.037      397912.148
#Sta/Elev= 30
       0 1100.04    39.0 1087.45    48.8 1082.60    58.5 1079.26    78.0 1075.04
    87.8 1073.63    97.5 1074.08   165.8 1062.27   175.5 1058.98   195.0 1054.74
   214.5 1045.83   234.0 1041.94   263.3 1042.85   273.0 1041.02   302.3 1032.62
   312.0 1031.18   331.5 1029.84   390.0 1028.46   480.1 1019.88   487.6 1019.49
   495.1 1019.91   536.4 1027.74   546.2 1028.71   644.0 1034.46   673.3 1037.14
   712.4 1038.82   761.3 1043.57   820.0 1052.79   849.3 1055.97   937.3 1074.82
#Mann= 3 , 0 , 0
       0     0.1       0   480.1   0.045       0   495.1     0.1       0
Bank Sta=   480.1,   495.1
Exp/Cntr=0.3,0.1

Type RM Length L Ch R = 1 ,249.5,268.073,225.492,214.959
XS GIS Cut Line= 3
     1755053.606      398530.196     1755598.304      398527.563
     1755992.677      398355.214
#Sta/Elev= 30
       0 1095.63    68.1 1095.11   107.0 1092.77   136.2 1093.70   214.0 1099.14
   223.7 1098.89   272.4 1092.84   340.4 1076.80   350.2 1073.74   379.3 1060.10
   389.1 1052.06   418.3 1035.60   447.4 1023.35   457.2 1020.80   486.3 1019.42
   521.1 1014.53   535.0 1013.88   536.1 1013.94   583.8 1018.53   603.4 1022.99
   642.5 1027.68   691.4 1026.95   750.1 1029.91   769.7 1031.77   789.2 1035.93
   808.8 1046.40   828.4 1054.96   838.2 1059.01   847.9 1060.72   975.1 1065.30
#Mann= 3 , 0 , 0
       0     0.1       0   521.1   0.045       0   536.1     0.1       0
Bank Sta=   521.1,   536.1
Exp/Cntr=0.3,0.1

Type RM Length L Ch R = 1 ,24,16.187,23.979,31.771
XS GIS Cut Line= 3
     1755222.108      399040.255     1755495.100      398843.834
     1755954.525      398540.880
#Sta/Elev= 30
       0 1038.01    19.2 1034.46    38.4 1035.07    96.1 1028.41   105.7 1028.85
   134.5 1026.28   288.3 1024.53   307.5 1022.70   326.7 1022.10   346.1 1016.78
   356.0 1016.08   385.4 1017.75   405.1 1019.98   424.8 1017.62   464.1 1021.17
   473.9 1020.53   493.5 1015.59   534.5 1007.67   542.7 1007.39   549.5 1007.85
   582.0 1011.24   621.3 1017.78   641.0 1020.26   670.4 1028.23   680.3 1030.02
   709.7 1032.80   768.7 1034.36   837.5 1030.96   847.3 1031.10   886.6 1034.45
#Mann= 3 , 0 , 0
       0     0.1       0   534.5   0.045       0   549.5     0.1       0
Bank Sta=   534.5,   549.5
Exp/Cntr=0.3,0.1